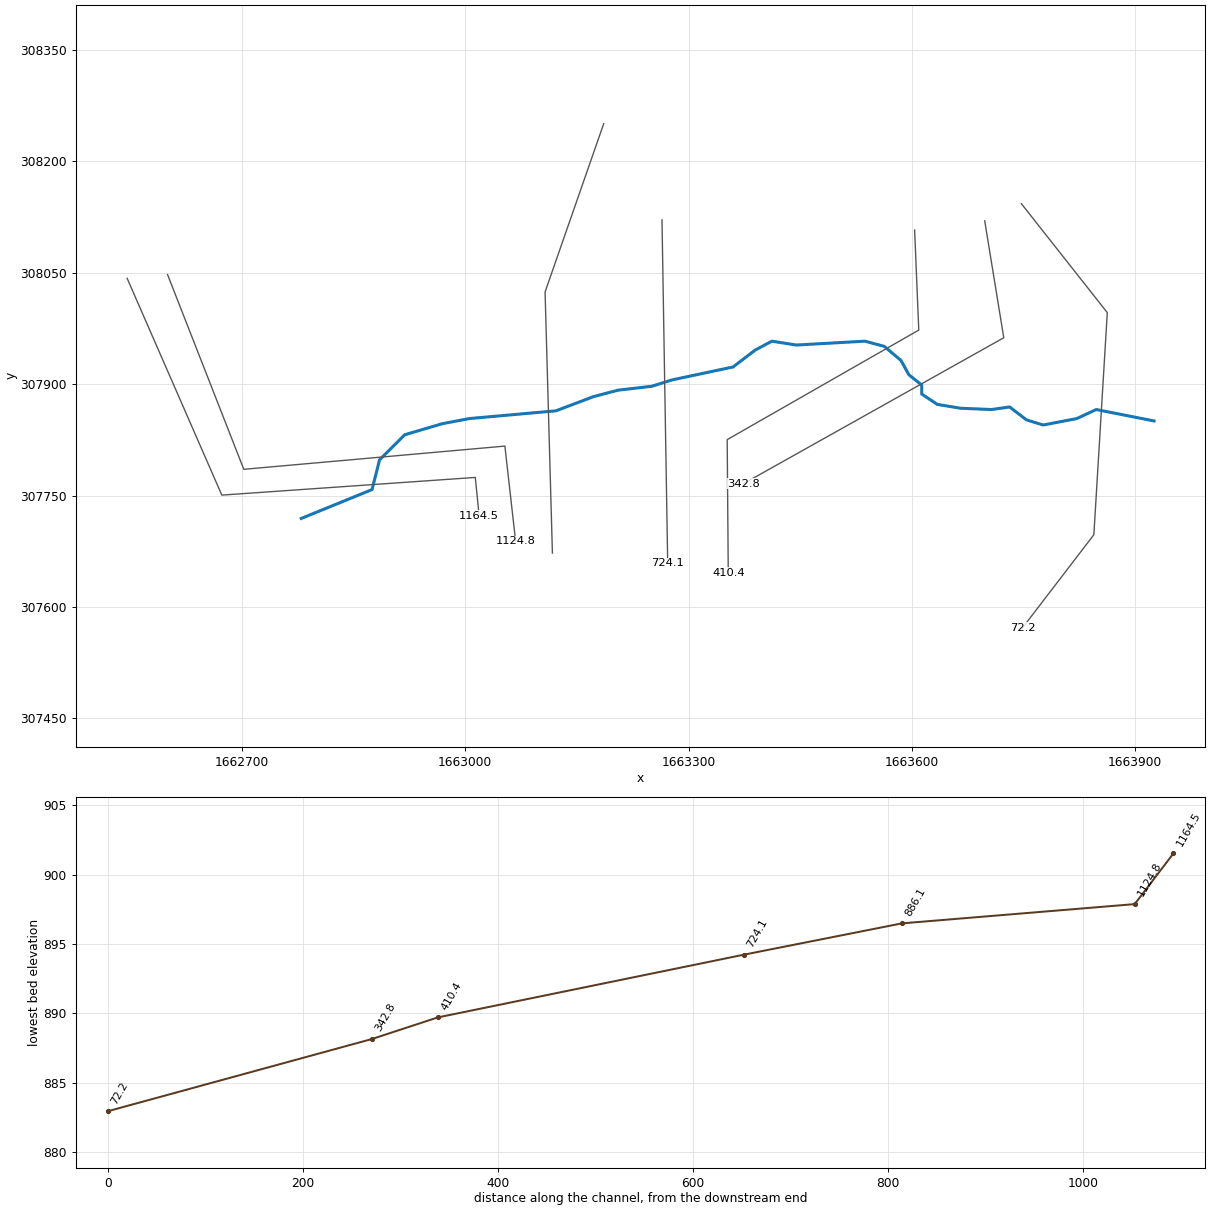
--- BIGRN.prj (project) ---

Proj Title=BIGRN
Current Plan=p01
Geom File=g01
Flow File=f01
Plan File=p01
DSS Export Rating Curves=0
DSS Export Rating Curve Sorted=0
DSS Export Volume Flow Curves=0
DXF OffsetX=0
DXF OffsetY=0
DXF ScaleX=0
DXF ScaleY=0

--- BIGRN.p01 (plan) ---

Plan Title=Floodplain
Program Version=4.00
Geom File=g01
Flow File=f01
K Sum by GR=0
Std Step Tol=0.01
Critical Tol=0.01
Num of Std Step Trials=20
Max Error Tol=0.3
Flow Tol Ratio=0.001
Split Flow NTrial=30
Split Flow Tol=0.02
Split Flow Ratio=0.02
Log Output Level=0
Friction Slope Method=1
Unsteady Friction Slope Method=2
Unsteady Bridges Friction Slope Method=1
Global Log Level=0
CheckData=False
Run HTab=0
Run UNet=0
Run PostProcess=0
UNET Theta=0
UNET Theta Warmup=0
UNET ZTol=0
UNET ZSATol=0
UNET MxIter=0
UNET MaxInSteps=0
UNET DtIC=0
UNET DtMin=0
UNET MaxCRTS=0
UNET WFStab=0
UNET SFStab=0
UNET WFX=0
UNET SFX=0
UNET DSS MLevel=0
UNET DZMax Abort=0
UNET Convert EG Bridges=0
UNET Use Existing IB Tables=0
UNET Froude Limit=0
UNET Froude Power=0
Write IC File=0
Echo Input=False
Echo Output=False
Write Detailed=0

--- BIGRN.f01 (steady flow) ---

Flow Title=NFF Regression Equation
Program Version=4.00
Number of Profiles=1
Profile Names=P100yr
River Rch & RM=BIGRN,Main      ,1164.5
511.7669
River Rch & RM=BIGRN,Main      ,410.4
565.5994
River Rch & RM=BIGRN,Main      ,72.2
568.3155
Boundary for River Rch & Prof#=BIGRN,Main      ,1
Up Type=0
Dn Type=3
Dn Slope=0.024378

--- BIGRN.g01 (geometry) ---

Geom Title=USGS 10m DEM
Program Version=4.10

River Reach=BIGRN           ,Main
Reach XY= 30
      1662779.65      307719.124     1662874.789      307758.013
     1662884.934      307798.044     1662918.645      307831.755
     1662969.101      307846.663      1663005.56      307853.607
     1663121.879      307864.024     1663172.226      307883.121
     1663205.212      307891.802     1663250.352       307897.01
     1663278.129      307905.691     1663359.726      307923.052
      1663389.24      307945.621      1663411.81      307957.774
     1663444.796      307952.566      1663536.81      307957.774
     1663562.851       307950.83     1663585.421      307931.732
     1663595.837      307912.635     1663613.199      307898.746
     1663613.199      307886.594     1663634.032      307872.704
     1663665.282      307867.496     1663706.949       307865.76
     1663731.254      307869.232     1663753.824      307851.871
     1663776.393      307844.927     1663821.532      307853.607
     1663847.574       307865.76     1663925.289      307850.384

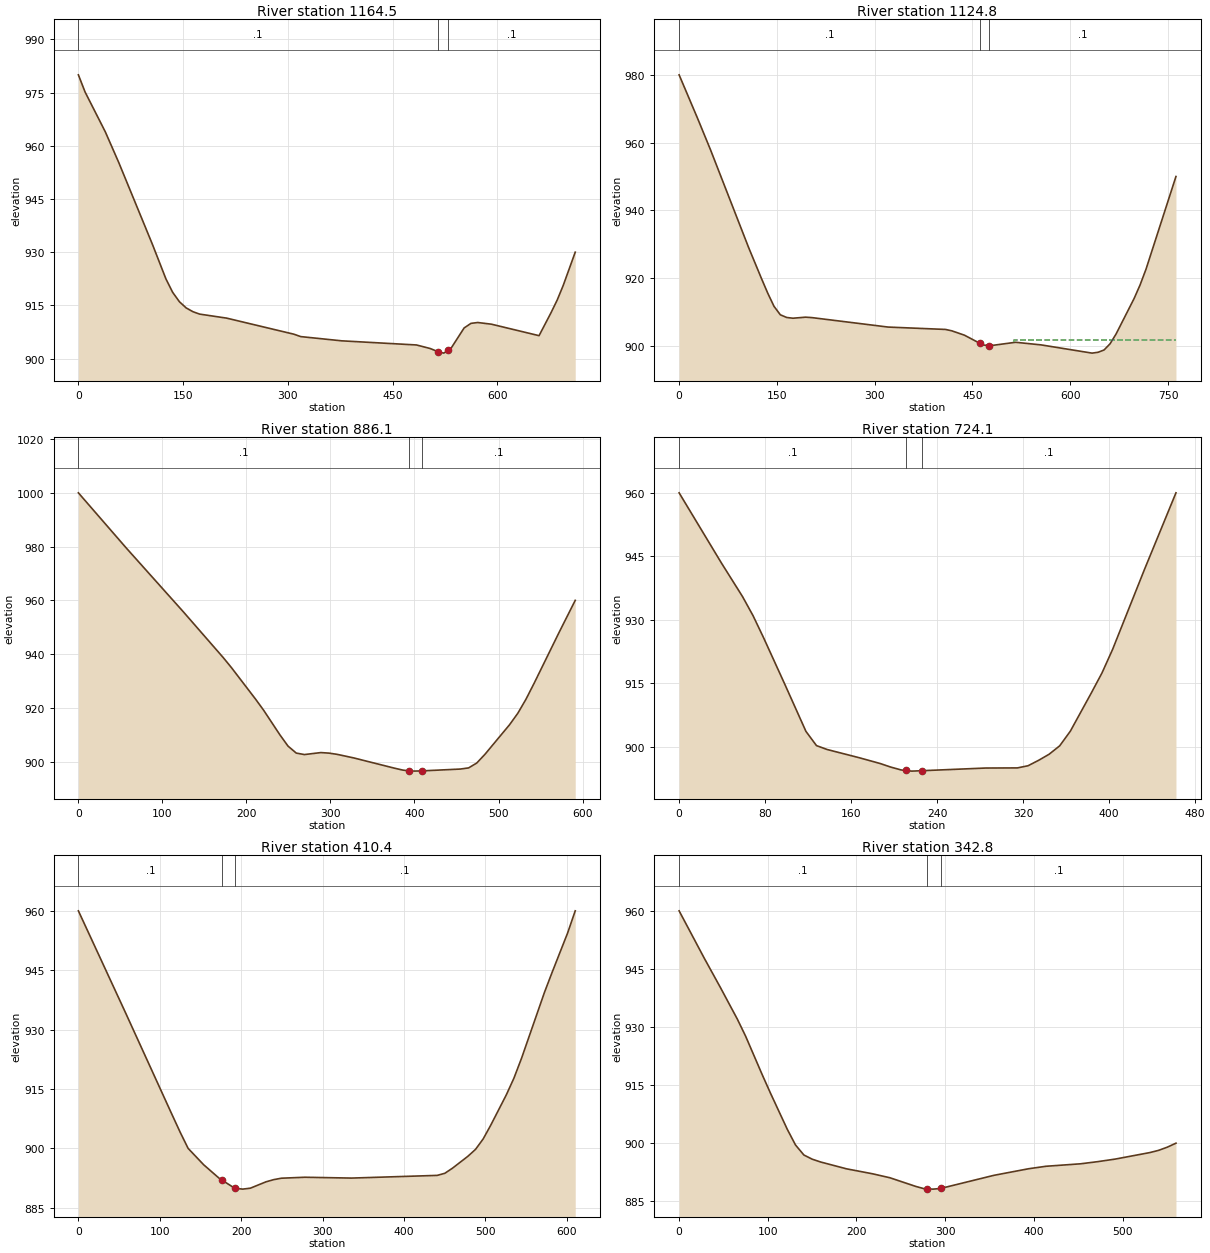
Type RM Length L Ch R = 1 ,1164.5  ,61.5,39.7,46.9
XS GIS Cut Line= 4
     1662545.858      308042.371     1662673.053      307750.582
     1663013.504      307774.367     1663018.676      307722.861
#Sta/Elev= 30
       0  979.99     9.6  975.14    38.6   963.9    57.9  955.23   106.1  932.16
   125.4  922.44     135  918.68   144.7  916.02   154.3  914.29     164  913.22
   173.6  912.54   212.2  911.41   308.7  906.87   318.3   906.2   376.8  905.01
   484.1  903.84   503.6  902.85   514.8  901.96   523.1  901.54   529.8  902.32
   532.8  902.67   552.3  908.63   562.1  909.93   571.8  910.17   591.3   909.7
   659.6  906.46   676.8  912.96   685.5  916.47   694.1  920.57   711.4     930
#Mann= 3 , 0 , 0
       0      .1       0   514.8    .045       0   529.8      .1       0
Bank Sta=514.8,529.8
XS Rating Curve= 0 ,0
Exp/Cntr=0.3,0.1

Type RM Length L Ch R = 1 ,1124.8  ,277.9,238.6,194.4
XS GIS Cut Line= 4
     1662600.134      308047.435     1662702.567      307785.305
     1663053.261      307816.555     1663067.677      307688.638
#Sta/Elev= 30
       0     980    29.1  966.81    48.5  957.72   106.8  928.96   126.2  919.97
   135.9  915.61   145.6  911.69   155.3  909.19     165   908.4   174.7  908.18
   194.1  908.49   203.8  908.36   320.6  905.57   408.6  904.87   418.4  904.46
   437.9  903.16   460.9  900.82   467.3  900.28   475.9  900.04   516.2  901.08
   555.3  900.31   633.5  897.88   642.7  898.13   651.9  898.81   661.1  900.63
   670.3  903.51   697.9  913.96   707.1  917.97   716.3  922.67   762.2     950
#Mann= 3 , 0 , 0
       0      .1       0   460.9    .045       0   475.9      .1       0
#XS Ineff= 2 , 0
                           513.8          901.63
Permanent Ineff=
       F       F
Bank Sta=460.9,475.9
XS Rating Curve= 0 ,0
Exp/Cntr=0.3,0.1

Type RM Length L Ch R = 1 ,886.1   ,162.4,162,161.6
XS GIS Cut Line= 3
     1663185.997      308250.464     1663107.257      308024.008
       1663117.1      307672.585
#Sta/Elev= 30
       0    1000    57.5   979.3   124.7  955.82   172.6  938.64   182.2  934.97
     211  923.21   220.6  919.08   239.8     910   249.5   905.8   259.3   903.2
     269  902.65   288.6  903.39   298.4  903.18   308.1  902.72   327.6  901.41
   376.5  897.56   386.2  896.87   393.4  896.59     396  896.49   408.4  896.57
   454.6  897.26   464.4  897.69   474.1   899.5   483.9  902.76   513.2  913.77
     523  918.03   532.7  923.25   542.5  929.25   571.8  947.91   591.3     960
#Mann= 3 , 0 , 0
       0      .1       0   393.4    .045       0   408.4      .1       0
Bank Sta=393.4,408.4
XS Rating Curve= 0 ,0
Exp/Cntr=0.3,0.1

Type RM Length L Ch R = 1 ,724.1   ,338.5,313.8,286
XS GIS Cut Line= 2
     1663264.311      308121.068     1663271.966        307658.9
#Sta/Elev= 28
       0     960    39.3  943.44      59  935.48    68.8  930.96    78.7  925.69
    98.4  914.72     118  903.62   127.8  900.26   137.7  899.34   167.2  897.42
   186.9  896.04   196.7   895.2   206.5  894.51   211.1  894.38   216.4  894.23
   226.1  894.33   285.2  894.96   314.7  894.99   324.6   895.5   334.4  896.78
   344.2  898.22     354   900.2   363.9  903.65   383.6  912.77   393.4  917.44
   403.2  922.96   432.7  941.76   462.2     960
#Mann= 3 , 0 , 0
       0      .1       0   211.1    .045       0   226.1      .1       0
Bank Sta=211.1,226.1
XS Rating Curve= 0 ,0
Exp/Cntr=0.3,0.1

Type RM Length L Ch R = 1 ,410.4   ,67.9,67.6,70.3
XS GIS Cut Line= 4
     1663603.655      308107.372      1663609.22      307972.714
     1663351.872      307825.235     1663353.317      307646.259
#Sta/Elev= 30
       0     960    57.8  934.31   115.5  908.32   125.2  904.01   134.8     900
   153.9  895.86     173  892.44   176.9  891.91   191.9  889.95   201.8   889.7
   211.3  889.94   230.4  891.54     240   892.1   249.6  892.46   278.3   892.7
   335.7  892.49   440.8  893.17   450.2   893.7   459.6  894.99   478.5  897.99
   487.9  899.74   497.3  902.38   506.7  905.89   525.6  913.46     535  917.69
   544.4  922.74   572.7  939.46   582.1  944.51     601  954.38   610.4     960
#Mann= 3 , 0 , 0
       0      .1       0   176.9    .045       0   191.9      .1       0
Bank Sta=176.9,191.9
XS Rating Curve= 0 ,0
Exp/Cntr=0.3,0.1

Type RM Length L Ch R = 1 ,342.8   ,248.1,270.6,292.7
XS GIS Cut Line= 3
     1663697.801      308119.776       1663723.4      307962.388
     1663374.021      307766.147
#Sta/Elev= 30
       0     960    28.1  947.88    46.9  940.06    65.7  932.02      75  927.63
    93.8  917.64   103.2  912.83   121.9  903.62   131.3  899.52   140.7  896.95
   150.1  895.87   159.5  895.15   188.8  893.38   218.1   892.1   237.6  891.08
     267  888.83   276.7  888.22   279.8  888.19   286.5  888.14   294.8  888.31
   354.9   891.7     394   893.4   413.6  894.04   452.7  894.68   472.2  895.24
   491.8   895.9   530.8  897.58   540.6  898.15   550.4  898.97   560.2     900
#Mann= 3 , 0 , 0
       0      .1       0   279.8    .045       0   294.8      .1       0
Bank Sta=279.8,294.8
XS Rating Curve= 0 ,0
Exp/Cntr=0.3,0.1

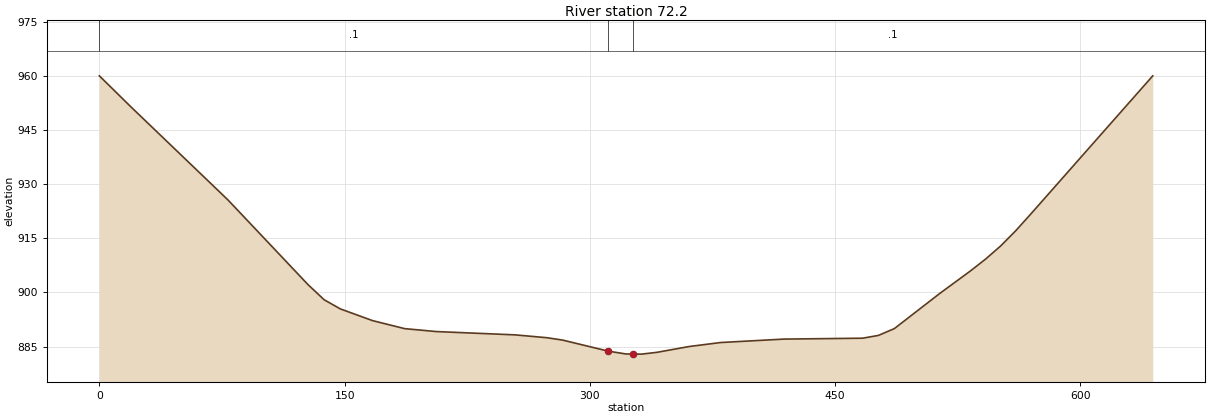
Type RM Length L Ch R = 1 ,72.2    ,75.2,72.2,69.1
XS GIS Cut Line= 4
     1663747.013      308142.872     1663862.466      307996.198
     1663844.403      307697.235      1663748.42      307571.725
#Sta/Elev= 30
       0     960    19.6  951.28    78.6  925.66   127.7  902.14   137.5  897.98
   147.4  895.45     167  892.22   186.7  889.99     206  889.18   254.3  888.26
   273.6  887.48   283.3  886.82   311.3  883.75   321.9  882.98   326.3  882.96
   331.6  882.93   341.2  883.44   360.6  885.03   379.9  886.14   418.5  887.09
   466.8  887.34   476.5  888.12   486.2     890     514  899.75   532.6  905.93
   541.9  909.22   551.2  912.88   560.5  917.14   569.8  921.82   644.2  959.99
#Mann= 3 , 0 , 0
       0      .1       0   311.3    .045       0   326.3      .1       0
Bank Sta=311.3,326.3
XS Rating Curve= 0 ,0
Exp/Cntr=0.3,0.1

Chan Stop Cuts=-1
Use User Specified Reach Order=0
Composite Channel Slope=5